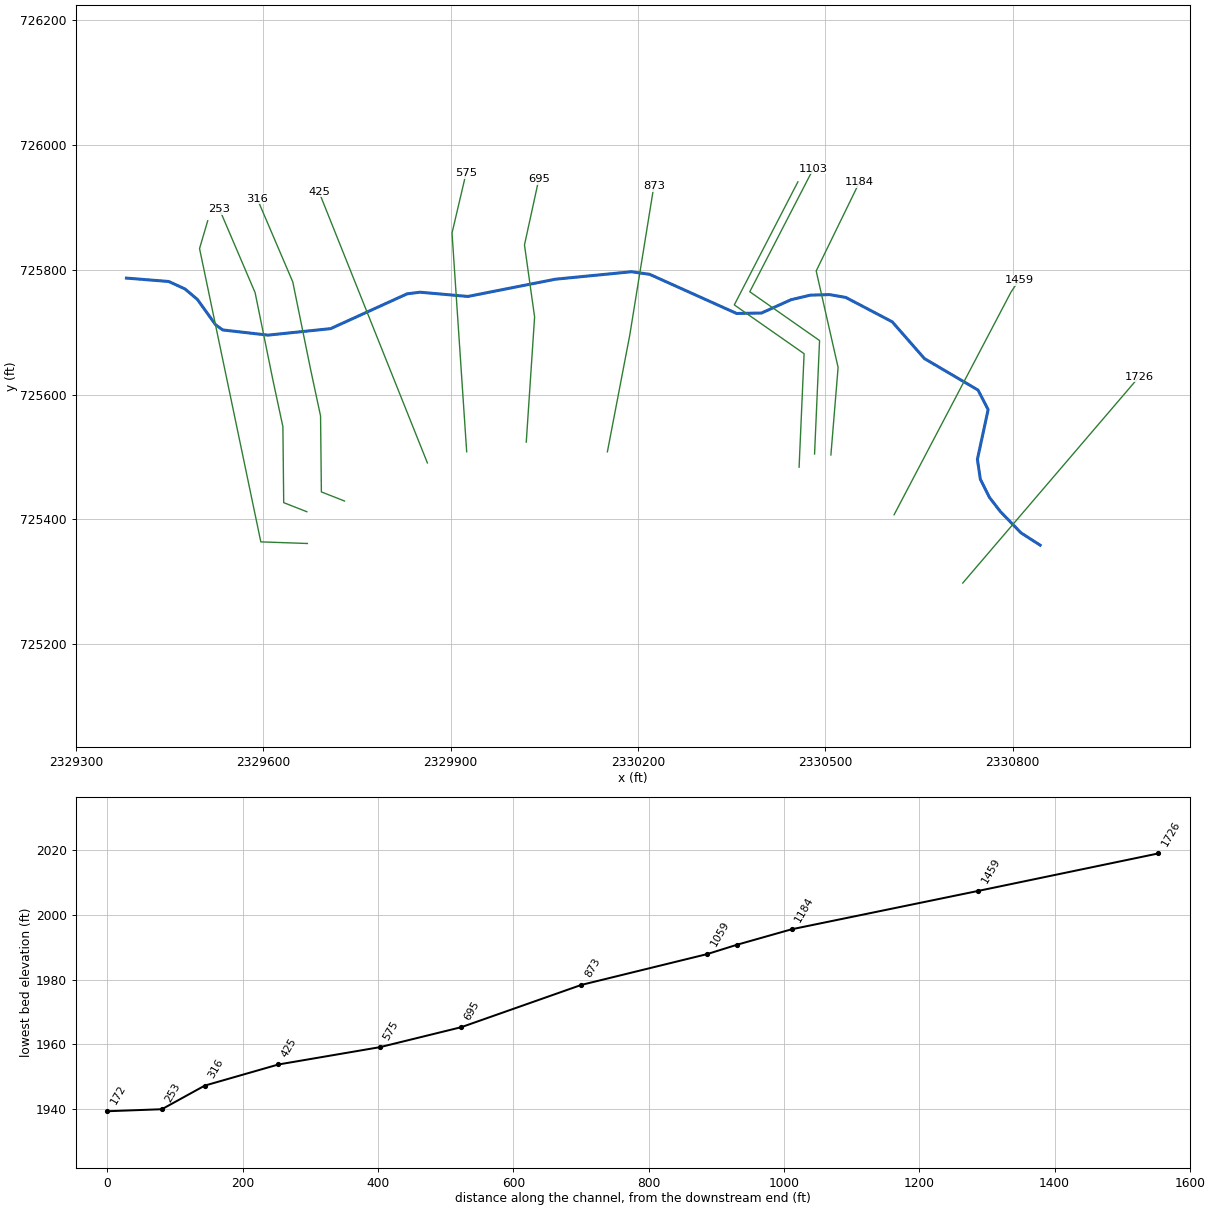
--- LILLAUREL2.prj (project) ---

Proj Title=LILLAUREL2
Current Plan=p01
Default Exp/Contr=0,0
English Units
Geom File=g01
Flow File=f01
Plan File=p01
BEGIN DESCRIPTION:
----------MODEL BY WOOD PLC 2022----------
AFH study
Randolph County, WV
HEC-RAS Version: RAS 6.2
Vertical Datum: NAVD88
Projection: NAD 1983 StatePlane West Virginia S FIPS 4702 (US Feet)
Terrain: 1-meter LIDAR (FEMA Region III 3DEP collected 2016-2018)
Land Use: 2019 NLCD
Hydrologic Method:
WV SIR2010-5033 regression equations
Additional Model Notes:
None
END DESCRIPTION:
DSS Export Rating Curves= 0
DSS Export Rating Curve Sorted= 0
DSS Export Volume Flow Curves= 0
DXF OffsetX= 0
DXF OffsetY= 0
DXF ScaleX= 0
DXF ScaleY= 0

--- LILLAUREL2.p01 (plan) ---

Plan Title=Floodplain
Program Version=6.20
Short Identifier=Floodplain
Geom File=g01
Flow File=f01
Subcritical Flow
K Sum by GR= 0
Std Step Tol= 0.01
Critical Tol= 0.01
Num of Std Step Trials= 20
Max Error Tol= 0.3
Flow Tol Ratio= 0.001
Split Flow NTrial= 30
Split Flow Tol= 0.02
Split Flow Ratio= 0.02
Log Output Level= 0
Friction Slope Method= 1
Unsteady Friction Slope Method= 2
Unsteady Bridges Friction Slope Method= 1
Parabolic Critical Depth
Global Vel Dist= 0 , 0 , 0
Global Log Level= 0
CheckData=True
Encroach Param=-1 ,0,0, 0
Mapping Interval=1HOUR
Computation Time Step Use Courant=        0
Computation Time Step Use Time Series=    0
Computation Time Step Count To Double=0
Computation Time Step Max Doubling=0
Computation Time Step Max Halving=0
Computation Time Step Residence Courant=0
Run HTab= 0
Run UNet= 0
Run Sediment= 0
Run PostProcess= 0
Run WQNet= 0
Run RASMapper=-1
UNET Theta= 0
UNET Theta Warmup= 0
UNET ZTol= 0
UNET ZSATol= 0
UNET MxIter= 0
UNET Max Iter WO Improvement= 0
UNET MaxInSteps= 0
UNET DtIC= 0
UNET DtMin= 0
UNET MaxCRTS= 0
UNET WFStab= 0
UNET SFStab= 0
UNET WFX= 1
UNET SFX= 1
UNET Gravity=32.174
UNET 1D Methodology=Finite Difference
UNET DSS MLevel= 1
UNET Pardiso=0
UNET DZMax Abort= 0
UNET Use Existing IB Tables= 0
UNET Froude Reduction=False
UNET Froude Limit= 0
UNET Froude Power= 0
UNET D1 Cores= 0
UNET WindReference=Eulerian
UNET WindDragFormulation=Hsu (1988)
UNET D2 Coriolis=0
UNET D2 Cores= 0
UNET D2 Theta= 1
UNET D2 Theta Warmup= 1
UNET D2 Z Tol= 0.01
UNET D2 Volume Tol= 0.01
UNET D2 Max Iterations= 20
UNET D2 Equation= 0
UNET D2 RampUpFraction=0.1
UNET D2 TimeSlices= 1
UNET D2 Turbulence Formulation=Non-Conservative (original)
UNET D2 Eddy Viscosity=0.3
UNET D2 Transverse Eddy Viscosity=0.1
UNET D2 Smagorinsky Mixing=0
UNET D2 BCVolumeCheck=0
UNET D2 Cores=0
UNET D2 SolverType=PARDISO (Direct)
UNET D2 Minimum Iterations= 2147483647
UNET D2 Maximum Iterations= 2147483647
UNET D2 Restart Number= 10
UNET D2 Relaxation Coeff=1.3
UNET D2 SOR Precondition Iterations= 10
UNET D2 ILUT Maximum Fill= 8
UNET D2 ILUT Tolerance=1E-08
UNET D1D2 MaxIter= 0
UNET D1D2 ZTol=0.01
UNET D1D2 QTol=0.1
UNET D1D2 MinQTol=1
Write IC File= 0
Write IC File at Fixed DateTime=0
Write IC File at Sim End=0
Echo Input=False
Echo Parameters=False
Echo Output=False
Write Detailed= 0
HDF Write Warmup=0
HDF Write Time Slices=0
HDF Flush=0
HDF Compression= 1
HDF Chunk Size= 1
HDF Spatial Parts= 1
HDF Use Max Rows=0
HDF Fixed Rows= 1
Calibration Method= 0
Calibration Iterations= 20
Calibration Max Change=0.05
Calibration Tolerance=0.2
Calibration Maximum=1.5
Calibration Minimum=0.5
Calibration Optimization Method= 1
WQ AD Non Conservative
WQ ULTIMATE=-1
WQ Max Comp Step=1HOUR
WQ Output Interval=15MIN
WQ Output Selected Increments= 0
WQ Output face flow=0
WQ Output face velocity=0
WQ Output face area=0
WQ Output face dispersion=0
WQ Output cell volume=0
WQ Output cell surface area=0
WQ Output cell continuity=0
WQ Output cumulative cell continuity=0
WQ Output face conc=0
WQ Output face dconc_dx=0
WQ Output face courant=0
WQ Output face peclet=0
WQ Output face adv mass=0
WQ Output face disp mass=0
WQ Output cell mass=0
WQ Output cell source sink temp=0
WQ Output nsm pathways=0
WQ Output nsm derived pathways=0
WQ Create Restart=0
WQ Fixed Restart=0
WQ System Summary=0
WQ Write To DSS=0
Sorting and Armoring Iterations= 10
XS Update Threshold= 0.02
Bed Roughness Predictor= 0
Hydraulics Update Threshold= 0.02
Energy Slope Method= 1
Volume Change Method= 1
Sediment Retention Method= 0
Sediment TS Multiplier= 1
Warm Up Method= 0
XS Weighting Method= 0
Number of US Weighted Cross Sections= 1
Number of DS Weighted Cross Sections= 1
Upstream XS Weight=0
Main XS Weight=1
Downstream XS Weight=0
Number of DS XS's Weighted with US Boundary= 1
Upstream Boundary Weight= 1
Weight of XSs Associated with US Boundary= 0
Number of US XS's Weighted with DS Boundary= 1
Downstream Boundary Weight= 0.5
Weight of XSs Associated with DS Boundary= 0.5
Percentile Method= 0
Sediment Output Level= 3
Mass or Volume Output= 0
Output Increment Type= 1
Profile and TS Output Increment= 1
Transport Output Increment 1
XS Output Flag= 0
XS Output Increment= 10
Read HDF5 Sediment Hotstart= 0
Sediment Hotstart Type= 0
Write Gradation File= 0
Read Gradation Hotstart= 0
Write HDF5 File= 1
Write Binary Output= 1
Write DSS Sediment File= 0
DSS Sediment Output Type= 1
SV Curve= 0
Specific Gage Flag= 0
Subcell Erosion Methods= 0
Subcell Deposition Methods= 0
Advection Scheme= 1
Matrix Solver= 0
Implicit Weighting Factor= 1
Maximum Outer Loop Convergence Iterations= 5
Convergence Maximum Absolute= 0.001
Convergence RMSE= 0.0001
Grain Fractions Max Abs Error= 0.001
Max Subgrid Regions= 1
Max Subgrid Length Scale= 3.402823E+38
Initial Layer Thickness= 3.402823E+38
Min Layer Thickness= 3.402823E+38
Max Layer Thickness= 3.402823E+38
Number of Layers= 5

--- LILLAUREL2.f01 (steady flow) ---

Flow Title=Flow
Program Version=4.00
Number of Profiles=1
Profile Names=P100yr
River Rch & RM=LILLAUREL2,Main,1726
     316
Boundary for River Rch & Prof#=LILLAUREL2,Main      ,1
Up Type=0
Dn Type=3
Dn Slope=0.05216

--- LILLAUREL2.g01 (geometry) ---

Geom Title=Geometry
Program Version=6.20

River Reach=LILLAUREL2      ,Main
Reach XY= 30
      2330844.27      725358.846     2330813.541      725378.637
     2330780.729      725412.491      2330763.02      725435.408
     2330748.437      725464.575      2330743.75      725496.345
     2330760.937      725576.033     2330744.791      725607.283
     2330658.854      725657.804     2330607.291      725716.658
 2330533.0464421725755.6303368472330507.01629122725760.239522813
2330476.14451227725759.354150881     2330445.312      725752.075
     2330397.916      725730.7212330358.03359298725730.031522812
      2330218.75        725792.7     2330189.616      725796.849
     2330067.708      725784.887     2329927.604      725757.283
     2329851.041      725764.054     2329830.208       725761.45
     2329707.812      725705.721     2329607.291      725695.304
     2329534.895      725703.637     2329523.437      725711.971
      2329494.27      725752.595     2329474.479      725769.262
     2329448.437      725781.241     2329380.679      725786.681

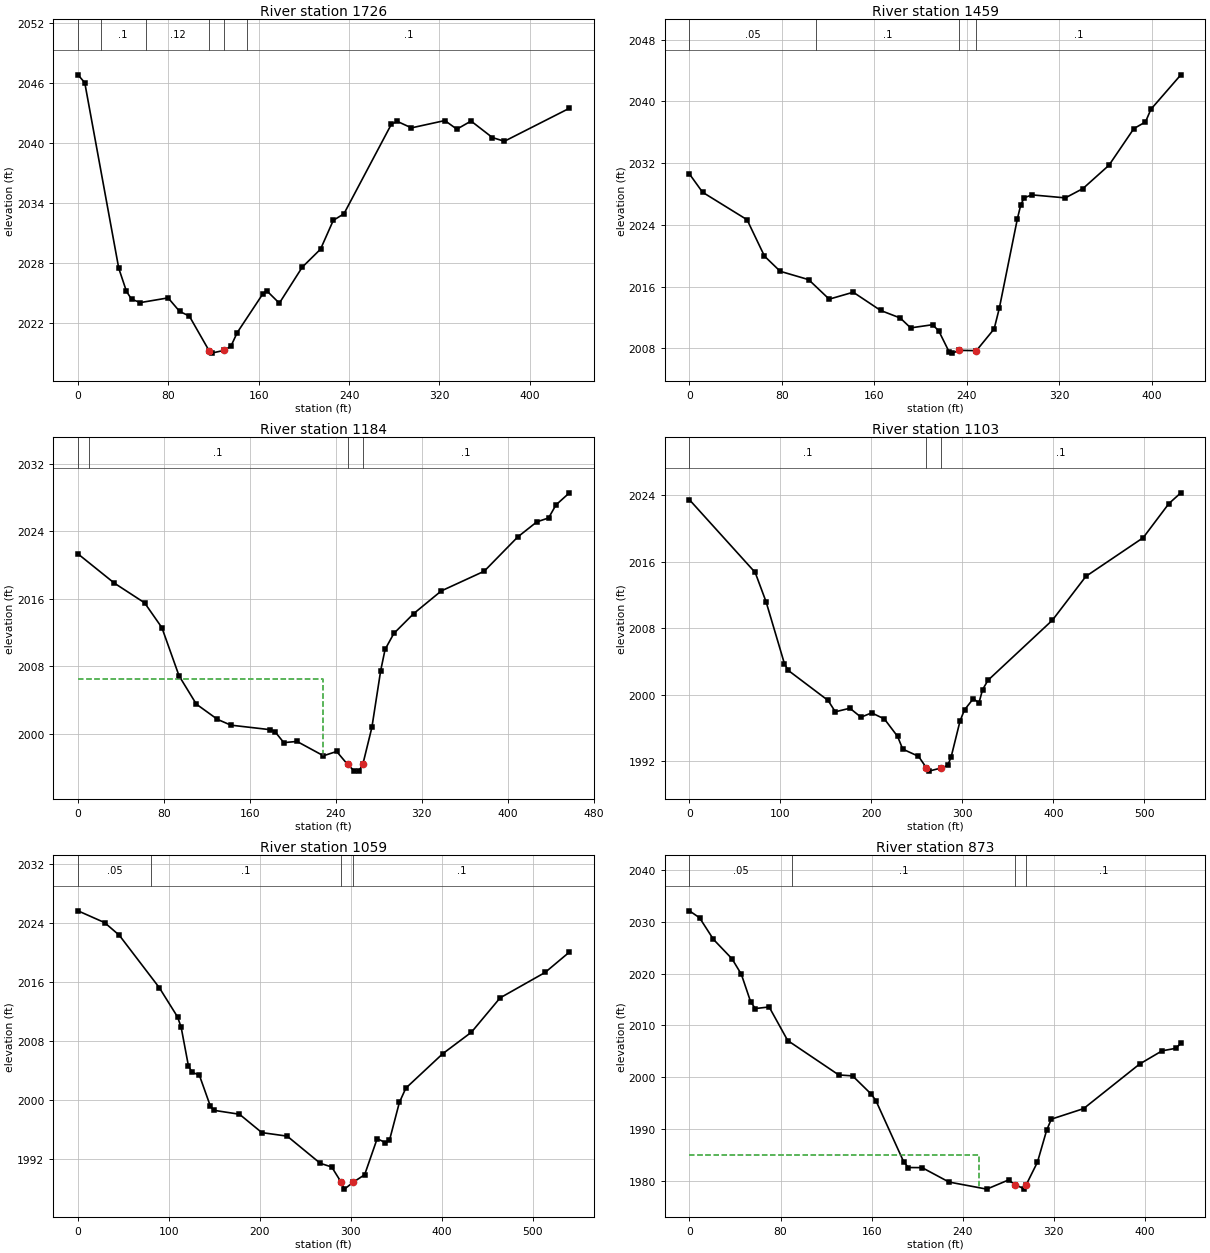
Type RM Length L Ch R = 1 ,1726    ,262,266.3,267
XS GIS Cut Line= 2
2330720.28768461725298.2303831752331003.14047983725628.998132771
#Sta/Elev= 30
       0 2046.78       6 2045.99    36.1 2027.45    42.9 2025.15    47.4 2024.36
    55.2 2024.02    79.8 2024.49      90 2023.14    98.6 2022.67  116.182019.195
   118.3 2018.97   129.1 2019.24   135.4 2019.65     141 2021.02   163.7 2024.89
     167 2025.22   178.3 2023.96   198.6 2027.56   214.8 2029.36   226.1 2032.24
   235.5 2032.89   277.6 2041.86   282.9 2042.12   295.3 2041.48   324.9 2042.21
   335.5 2041.35   348.1 2042.16     367 2040.51   377.6 2040.14   435.2 2043.44
#Mann= 6 ,-1,0
       0     .05       0      20      .1       0      60     .12       0
  116.18    .045       0   129.1     .12       0     150      .1       0
Bank Sta=116.18,129.1
XS Rating Curve= 0 ,0
Exp/Cntr(USF)=0,0
Exp/Cntr=0.3,0.1

Type RM Length L Ch R = 1 ,1459    ,268.8,275.9,278.6
XS GIS Cut Line= 3
2330610.31554925725407.6324212932330797.56986909 725764.24195562
2330810.19477722725783.026178115
#Sta/Elev= 30
       0 2030.61    11.4 2028.24    49.9 2024.68      65 2019.96    78.6    2018
   103.2 2016.92     121 2014.39   141.8 2015.29   165.5 2012.93   182.5 2011.95
   191.5 2010.67   210.5 2011.08   215.8 2010.29   224.7  2007.6   227.7  2007.4
   233.6 2007.76   248.4 2007.72   263.8 2010.54   268.3 2013.24   283.9  2024.8
   286.9 2026.65   289.9 2027.53   296.5  2027.9   325.4 2027.51   340.6 2028.71
   363.2 2031.74   384.7 2036.48   394.8 2037.35   399.5 2038.99   425.4 2043.45
#Mann= 4 ,-1,0
       0     .05       0     110      .1       0   233.6    .045       0
   248.4      .1       0
Bank Sta=233.6,248.4
XS Rating Curve= 0 ,0
Exp/Cntr(USF)=0,0
Exp/Cntr=0.3,0.1

Type RM Length L Ch R = 1 ,1184    ,73.5,80.7,84.7
XS GIS Cut Line= 4
2330509.07670667725503.3643542372330520.61697817725643.561634638
 2330485.5246967725798.0886110832330554.89495473725940.450975302
#Sta/Elev= 30
       0  2021.3    33.9 2017.83      62  2015.5    78.1 2012.56    94.1 2006.84
   110.2 2003.49   129.8 2001.69   142.3    2001   179.2 2000.46   183.3 2000.24
   191.6 1998.93   203.9 1999.07   228.5 1997.37   240.8 1997.88     251 1996.34
   257.2 1995.58   261.3 1995.55  265.14 1996.34   273.6 2000.73   281.8 2007.47
   285.9 2009.98   294.1 2011.88   312.4 2014.21   338.2 2016.91   378.2 2019.25
   409.4 2023.31   427.2  2025.1   438.1 2025.56     445 2027.11   457.5 2028.54
#Mann= 4 ,-1,0
       0     .05       0      10      .1       0     251    .045       0
  265.14      .1       0
#XS Ineff= 2 , 0
          228.37 2006.45
Permanent Ineff=
       F       F
Bank Sta=251,265.14
XS Rating Curve= 0 ,0
Exp/Cntr(USF)=0,0
Exp/Cntr=0.3,0.1

Type RM Length L Ch R = 1 ,1103    ,48.9,44,46.6
XS GIS Cut Line= 4
2330482.90299398725504.9189652642330490.92453988725686.631439259
2330379.13954818725764.8143947612330480.99381288725961.935377268
#Sta/Elev= 30
       0 2023.49    72.3 2014.72    84.3 2011.18   104.4 2003.75   108.4 2002.94
   152.4  1999.3   160.4 1997.93   176.4 1998.36   188.6 1997.28   200.3  1997.8
   214.3 1997.07   228.8 1994.97   234.5 1993.43   251.8 1992.57  260.58 1991.17
   263.3 1990.78   277.1 1991.17     284 1991.48   287.8 1992.53   297.5 1996.83
   302.4 1998.17     312  1999.5   318.3 1999.02   322.3 2000.61   328.2 2001.73
     399 2008.97   435.8 2014.25   498.8 2018.91   527.1 2023.03   540.2 2024.32
#Mann= 3 ,0,0
       0      .1       0  260.58    .045       0   277.1      .1       0
Bank Sta=260.58,277.1
XS Rating Curve= 0 ,0
Exp/Cntr(USF)=0,0
Exp/Cntr=0.3,0.1

Type RM Length L Ch R = 1 ,1059    ,188.4,186.1,176.6
XS GIS Cut Line= 4
 2330458.1311987  725483.86779442330466.15274459725665.580268395
 2330354.3677529725743.763223897 2330456.2220176725940.884206403
#Sta/Elev= 30
       0 2025.62    29.3 2024.02    45.4 2022.31    89.4  2015.2   109.4 2011.25
   113.4 2009.84   121.4  2004.6   125.4 2003.74   133.4 2003.35   145.5 1999.15
   149.5 1998.58   177.5 1998.05   202.1 1995.56     230 1995.08   266.3  1991.4
   278.9  1990.9  289.13 1988.87   292.9  1987.9   302.7 1988.85   315.1 1989.85
   328.9 1994.75   337.9 1994.19   342.4 1994.52   353.3 1999.66   360.4 2001.59
   400.8 2006.24   432.5 2009.17     464 2013.82   513.5 2017.27   540.2 2020.03
#Mann= 4 ,-1,0
       0     .05       0      80      .1       0  289.13    .045       0
   302.7      .1       0
Bank Sta=289.13,302.7
XS Rating Curve= 0 ,0
Exp/Cntr(USF)=0,0
Exp/Cntr=0.3,0.1

Type RM Length L Ch R = 1 ,873     ,175.6,177.4,178.7
XS GIS Cut Line= 3
2330151.06757337725508.4397648452330186.89921947725695.272801849
2330225.40534802725933.419513238
#Sta/Elev= 30
       0 2032.11     8.9 2030.77    21.1  2026.6    37.4 2022.85    45.6 2019.86
    53.7 2014.59    57.8 2013.24      70 2013.55    86.3 2007.07   131.1 2000.43
   143.3 2000.24   159.6 1996.73   163.7 1995.49   188.1 1983.68   192.2 1982.55
   204.3 1982.53   227.9 1979.75   261.1 1978.38   280.2 1980.15286.11011979.212
   293.5 1978.49295.83971979.272   305.6 1983.59   313.7 1989.77   317.8 1991.89
   346.1 1993.92   395.3 2002.53     415 2005.08   427.2 2005.57   431.5 2006.55
#Mann= 4 ,-1,0
       0     .05       0      90      .1       0286.1101    .045       0
295.8397      .1       0
#XS Ineff= 2 , 0
          254.24 1985.01
Permanent Ineff=
       F       F
Bank Sta=286.1101,295.8397
XS Rating Curve= 0 ,0
Exp/Cntr(USF)=0,0
Exp/Cntr=0.3,0.1

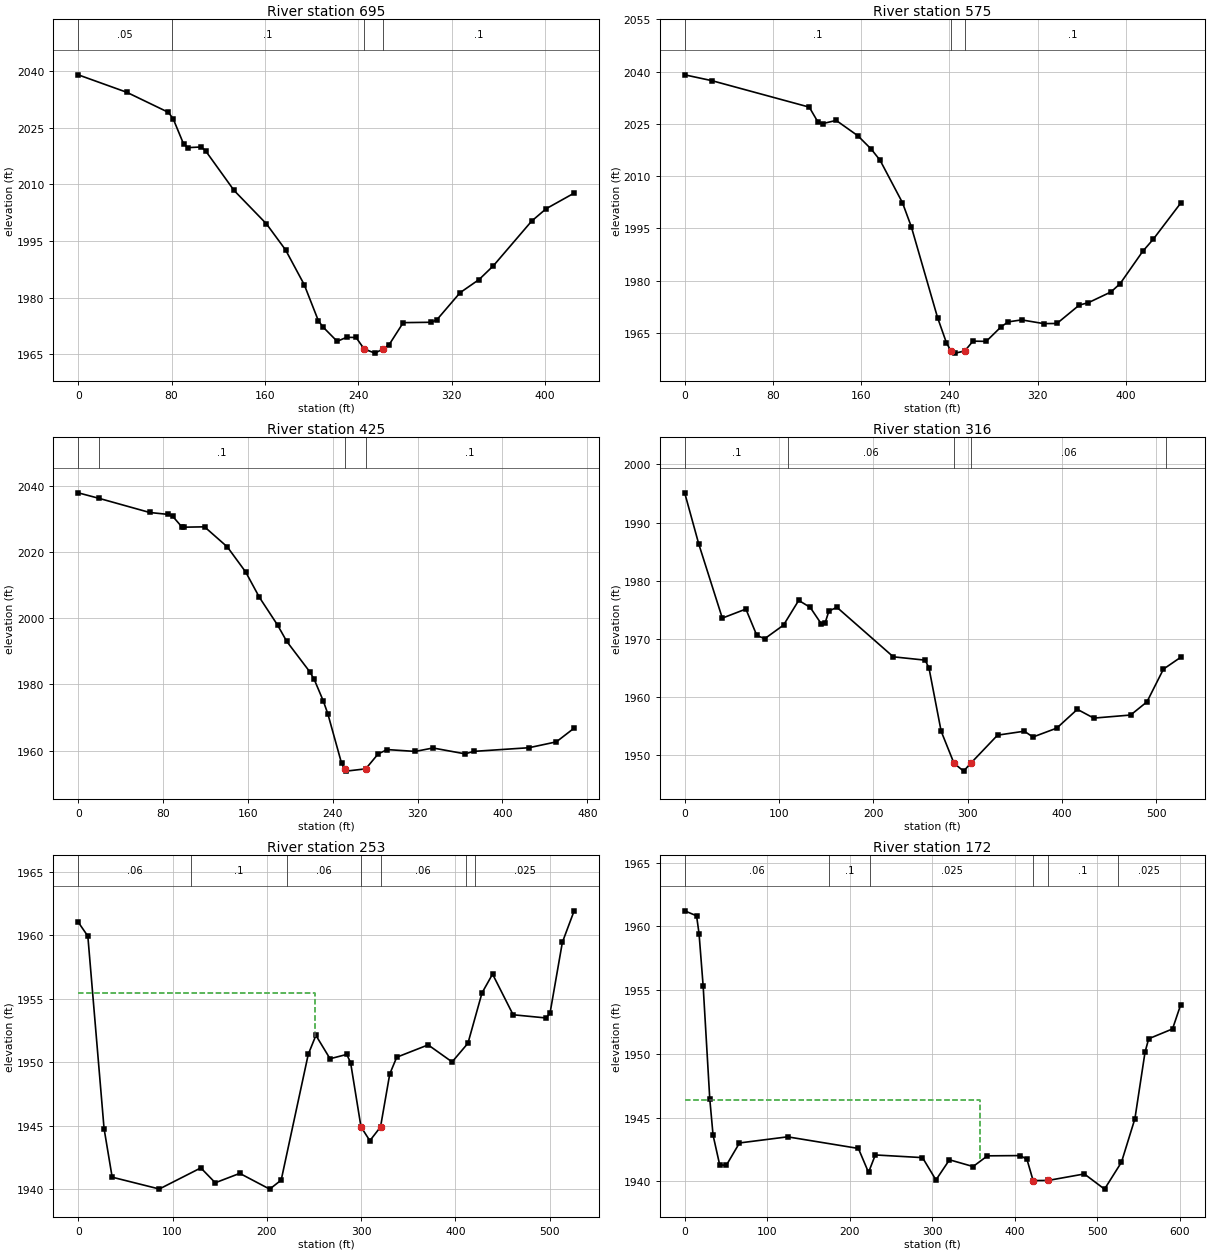
Type RM Length L Ch R = 1 ,695     ,120.6,120.1,119.8
XS GIS Cut Line= 4
2330021.11808915725524.0009861252330034.47550375 725724.36220516
2330018.25578602725839.8084313662330041.15421106725944.759546099
#Sta/Elev= 30
       0 2039.01    41.6 2034.39    77.3 2029.07    81.4 2027.32    90.4  2020.6
    94.2 2019.74   105.4 2019.91   109.2 2018.85   133.5  2008.4   161.2 1999.57
   177.6 1992.67   193.6 1983.46   205.7 1973.92   209.7 1972.25   221.8 1968.46
   229.9 1969.53     238 1969.48  244.93 1966.44   254.1 1965.34  260.821966.377
   266.3 1967.56   278.4 1973.41   302.6 1973.51   307.2 1974.17   327.1 1981.34
   343.4 1984.83   355.6 1988.46   388.4 2000.29   400.8 2003.56   424.8  2007.7
#Mann= 4 ,-1,0
       0     .05       0      80      .1       0  244.93    .045       0
  260.82      .1       0
Bank Sta=244.93,260.82
XS Rating Curve= 0 ,0
Exp/Cntr(USF)=0,0
Exp/Cntr=0.3,0.1

Type RM Length L Ch R = 1 ,575     ,146.9,150.1,152.5
XS GIS Cut Line= 3
2329925.67637727725508.4921953572329902.19998664725858.891141028
2329924.67671254725954.575662099
#Sta/Elev= 30
       0 2039.05    24.6 2037.38   112.9 2029.78     121 2025.38     125 2025.04
   137.3 2025.97     157 2021.55   169.1 2017.72   177.1 2014.53   197.4 2002.34
   205.4 1995.47   229.2 1969.38   237.2 1962.19   241.2 1959.83   245.2 1959.18
   253.8 1959.78   261.3 1962.62   273.3 1962.55     287  1966.8   293.3 1968.15
   305.4 1968.72   325.4 1967.65   337.4 1967.69   357.6 1972.96   365.9 1973.66
   386.4 1976.74   394.7 1979.13   415.2 1988.41   424.6 1991.83   449.5  2002.2
#Mann= 3 ,-1,0
       0      .1       0   241.2    .045       0   253.8      .1       0
Bank Sta=241.2,253.8
XS Rating Curve= 0 ,0
Exp/Cntr(USF)=0,0
Exp/Cntr=0.3,0.1

Type RM Length L Ch R = 1 ,425     ,110.8,108.9,107.6
XS GIS Cut Line= 2
2329862.73731601725490.6074496192329689.09092618725924.723424195
#Sta/Elev= 30
       0 2037.89      20 2036.19    67.4 2031.95    84.6 2031.38    88.9 2030.87
    97.5 2027.68    99.3 2027.51   119.1 2027.62   140.6 2021.55   157.9 2013.98
   170.8 2006.34     188 1997.93   196.6 1993.02   218.2 1983.89   222.5 1981.54
   231.1 1975.01   235.4 1971.09   248.3  1956.2   251.3 1954.54   252.6 1953.83
  271.09 1954.52   282.8 1959.03   291.4 1960.34   317.8 1959.78   334.5 1960.82
   364.7 1959.05   373.1  1959.8     425  1960.9   450.8 1962.67   467.6 1966.82
#Mann= 4 ,-1,0
       0     .05       0      20      .1       0   251.3    .045       0
  271.09      .1       0
Bank Sta=251.3,271.09
XS Rating Curve= 0 ,0
Exp/Cntr(USF)=0,0
Exp/Cntr=0.3,0.1

Type RM Length L Ch R = 1 ,316     ,63.3,63.4,63.8
XS GIS Cut Line= 6
  2329730.022171725429.5912550192329692.92822358725444.166667391
  2329691.619443725565.8832613572329675.91407603725639.174973853
2329647.12090327725780.5232765232329590.12898758725913.879781077
#Sta/Elev= 30
       0 1995.13    14.9 1986.35    39.9  1973.6    64.9 1975.16    76.5 1970.62
    84.9 1970.07   104.8  1972.4   120.9 1976.65   133.1 1975.44   144.9  1972.6
   148.9 1972.78   152.9 1974.82   161.4 1975.46   221.2 1966.95   254.9 1966.38
     259 1965.04   271.9 1954.17   285.5 1948.67   295.7 1947.31  303.42 1948.68
   331.7 1953.49   360.1 1954.17   369.2 1953.17   394.5  1954.7   416.3 1957.93
   433.7 1956.42   472.8 1956.95   490.1 1959.21   507.6 1964.84   525.8 1966.86
#Mann= 5 ,-1,0
       0      .1       0  109.85     .06       0   285.5    .045       0
  303.42     .06       0  510.79      .1       0
Bank Sta=285.5,303.42
XS Rating Curve= 0 ,0
Exp/Cntr(USF)=0,0
Exp/Cntr=0.3,0.1

Type RM Length L Ch R = 1 ,253     ,81.5,80.6,81.6
XS GIS Cut Line= 6
2329669.68513452725412.418137164 2329632.5911871725426.993549536
2329631.28240652725548.7101435022329615.57703956725622.001855997
2329586.78386679725763.3501586682329529.79195111725896.706663222
#Sta/Elev= 30
       0 1961.03    10.2 1959.93    27.4 1944.79      36 1940.96      86 1940.03
     130 1941.69   145.3 1940.52   171.3 1941.26     203 1940.02   215.2 1940.73
   243.9 1950.63     252 1952.12     267 1950.28   284.7 1950.62   288.8 1949.97
   299.8 1944.92   309.2 1943.83   320.5 1944.91   330.3 1949.08   337.7  1950.4
     371 1951.37   396.4 1950.03   413.2  1951.5   428.1 1955.46   439.3 1956.94
   461.1 1953.74   495.9 1953.49   500.2 1953.86   513.3 1959.44   525.8 1961.92
#Mann= 7 ,-1,0
       0     .06       0  119.85      .1       0  221.58     .06       0
   299.8    .045       0   320.5     .06       0  410.79      .1       0
  420.79    .025       0
#XS Ineff= 2 , 0
          251.26 1955.43
Permanent Ineff=
       F       F
Bank Sta=299.8,320.5
XS Rating Curve= 0 ,0
Exp/Cntr(USF)=0,0
Exp/Cntr=0.3,0.1

Type RM Length L Ch R = 1 ,172     ,,,
XS GIS Cut Line= 4
2329670.54582393725361.5545205212329595.94533086725364.172081682
2329497.78678733725834.0243100032329510.87459314725878.522849733
#Sta/Elev= 30
       0 1961.22    14.4 1960.83    17.4 1959.44    22.4 1955.31    30.4 1946.48
    34.4 1943.63    42.4 1941.31    50.4 1941.26    66.4 1943.02   124.7  1943.5
   210.5 1942.59   222.8 1940.71     231 1942.08   288.2 1941.87   304.5 1940.12
   320.9  1941.7   349.5 1941.17   366.9 1942.01   406.8 1942.03   414.8 1941.73
  422.25 1940.07   440.4 1940.08   484.3 1940.59   508.8  1939.4   529.3 1941.51
   545.6 1944.92   557.9 1950.15   562.3 1951.19   591.2 1951.96     601 1953.84
#Mann= 6 ,-1,0
       0     .06       0  174.65      .1       0  224.65    .025       0
  422.25    .045       0   440.4      .1       0  524.65    .025       0
#XS Ineff= 2 , 0
          358.34 1946.38
Permanent Ineff=
       F       F
Bank Sta=422.25,440.4
XS Rating Curve= 0 ,0
Exp/Cntr(USF)=0,0
Exp/Cntr=0.3,0.1
LCMann Table=0

Chan Stop Cuts=-1
Use User Specified Reach Order=0
Composite Channel Slope=5